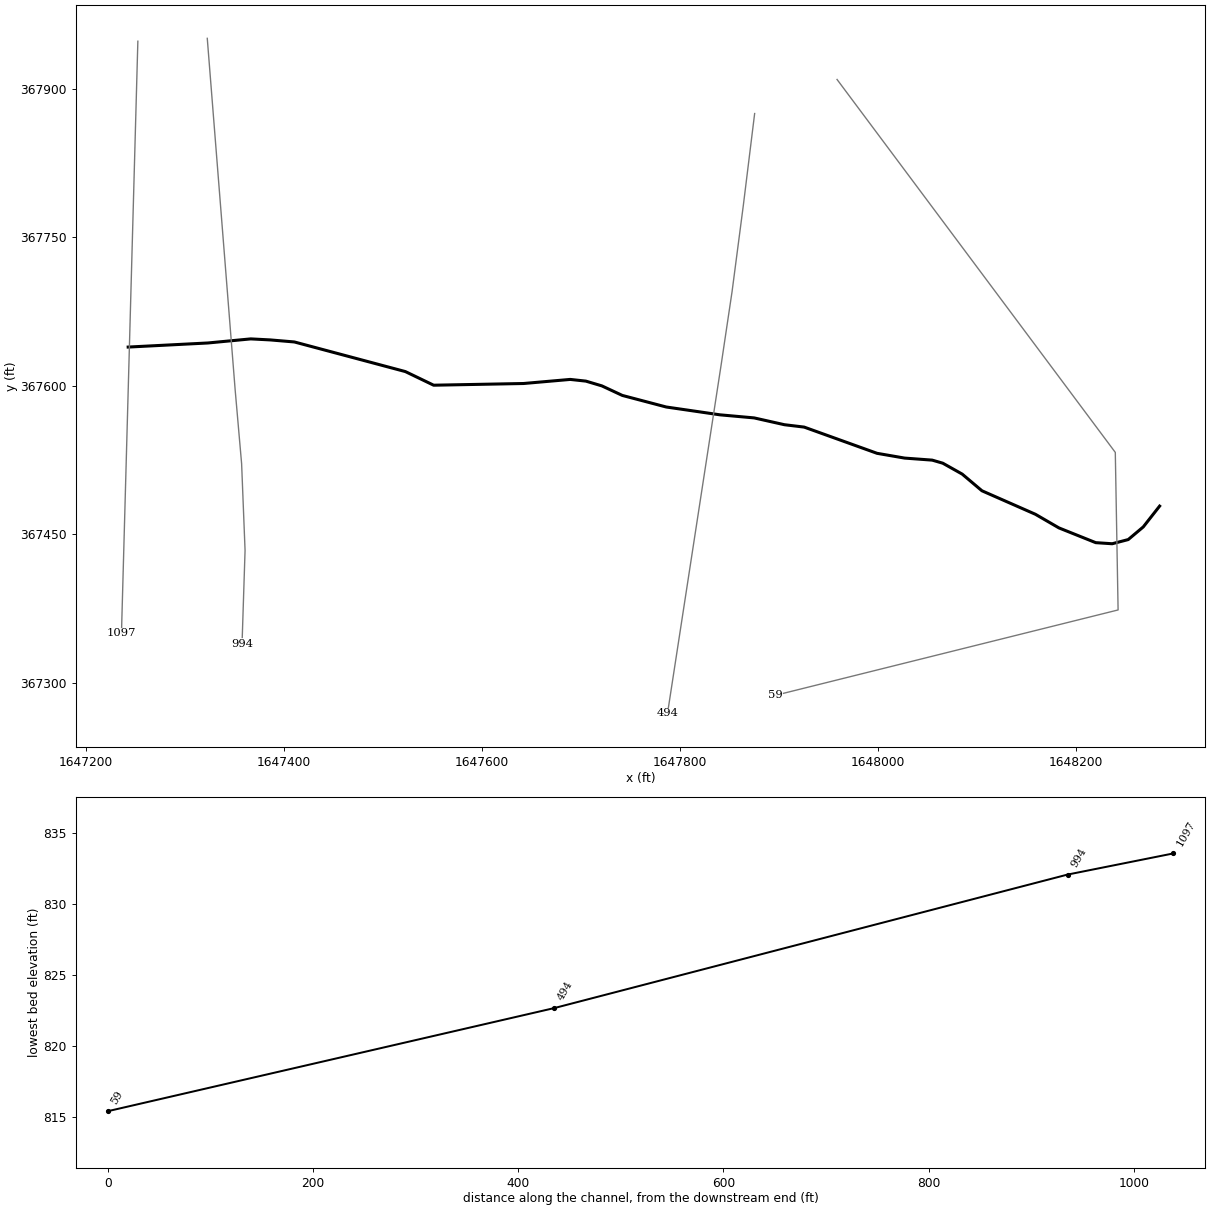
--- BUFALORNT2.prj (project) ---

Proj Title=BUFALORNT2
Current Plan=p01
Default Exp/Contr=0.3,0.1
English Units
Geom File=g01
Flow File=f01
Plan File=p01
Y Axis Title=Elevation
X Axis Title(PF)=Main Channel Distance
X Axis Title(XS)=Station
BEGIN DESCRIPTION:
---------- MODELED AS PART OF WVEMD CTP PROGRAM, 2023----------
Stream Name: Buffalo Run Tributary 2
Flood Zone:  AFH
Wetzel County, WV
HEC-RAS Version: RAS 6.3
Vertical Datum: NAVD88
Projection: NAD 1983 StatePlane West Virginia S FIPS 4702 (US Feet)
Terrain: 1-meter West Virginia FEMA R3 South Central (collected 2018-2020)
Land Use: 2019 NLCD
Hydrologic Method:
WV 2010 Regional Regression Equations
Additional Model Notes:
None
END DESCRIPTION:
DSS Export Rating Curves= 0
DSS Export Rating Curve Sorted= 0
DSS Export Volume Flow Curves= 0
DXF OffsetX= 0
DXF OffsetY= 0
DXF ScaleX= 1
DXF ScaleY= 10

--- BUFALORNT2.p01 (plan) ---

Plan Title=Floodplain
Program Version=6.31
Short Identifier=Floodplain
Geom File=g01
Flow File=f01
Subcritical Flow
K Sum by GR= 0
Std Step Tol= 0.01
Critical Tol= 0.01
Num of Std Step Trials= 20
Max Error Tol= 0.3
Flow Tol Ratio= 0.001
Split Flow NTrial= 30
Split Flow Tol= 0.02
Split Flow Ratio= 0.02
Log Output Level= 0
Friction Slope Method= 1
Unsteady Friction Slope Method= 2
Unsteady Bridges Friction Slope Method= 1
Parabolic Critical Depth
Global Vel Dist= 0 , 0 , 0
Global Log Level= 0
CheckData=True
Encroach Param=-1 ,0,0, 0
Computation Interval=1MIN
Output Interval=1HOUR
Instantaneous Interval=1HOUR
Mapping Interval=1HOUR
Computation Time Step Use Courant=        0
Computation Time Step Use Time Series=    0
Computation Time Step Count To Double=0
Computation Time Step Max Doubling=0
Computation Time Step Max Halving=0
Computation Time Step Residence Courant=0
Run HTab= 0
Run UNet= 0
Run Sediment= 0
Run PostProcess= 0
Run WQNet= 0
Run RASMapper= 0
UNET Theta= 1
UNET Theta Warmup= 1
UNET ZTol= 0.02
UNET ZSATol= 0.02
UNET MxIter= 20
UNET Max Iter WO Improvement= 0
UNET MaxInSteps= 0
UNET DtIC= 0
UNET DtMin= 0
UNET MaxCRTS= 20
UNET WFStab= 2
UNET SFStab= 1
UNET WFX= 1
UNET SFX= 1
UNET Gravity=32.17405
UNET 1D Methodology=Finite Difference
UNET DSS MLevel= 4
UNET Pardiso=0
UNET DZMax Abort= 100
UNET Use Existing IB Tables=-1
UNET Froude Reduction=False
UNET Froude Limit= 0.8
UNET Froude Power= 4
UNET D1 Cores= 0
UNET WindReference=Eulerian
UNET WindDragFormulation=Hsu (1988)
UNET D2 Coriolis=0
UNET D2 Cores= 0
UNET D2 Theta= 1
UNET D2 Theta Warmup= 1
UNET D2 Z Tol= 0.01
UNET D2 Volume Tol= 0.01
UNET D2 Max Iterations= 20
UNET D2 Equation= 0
UNET D2 RampUpFraction=0.1
UNET D2 TimeSlices= 1
UNET D2 Turbulence Formulation=None
UNET D2 Eddy Viscosity=0.3
UNET D2 Transverse Eddy Viscosity=0.1
UNET D2 Smagorinsky Mixing=0.05
UNET D2 BCVolumeCheck=0
UNET D2 Cores=0
UNET D2 SolverType=PARDISO (Direct)
UNET D2 Minimum Iterations= 3
UNET D2 Maximum Iterations= 30
UNET D2 Restart Number= 10
UNET D2 Relaxation Coeff=1.3
UNET D2 SOR Precondition Iterations= 10
UNET D2 ILUT Maximum Fill= 8
UNET D2 ILUT Tolerance=1E-08
UNET D2 Convergence Tolerance=0.00001
UNET D1D2 MaxIter= 0
UNET D1D2 ZTol=0.01
UNET D1D2 QTol=0.1
UNET D1D2 MinQTol=1
Write IC File= 0
Write IC File at Fixed DateTime=0
Write IC File at Sim End=0
Echo Input=False
Echo Parameters=False
Echo Output=False
Write Detailed= 0
HDF Write Warmup=0
HDF Write Time Slices=0
HDF Flush=0
HDF Compression= 1
HDF Chunk Size= 1
HDF Spatial Parts= 1
HDF Use Max Rows=0
HDF Fixed Rows= 1
Calibration Method= 0
Calibration Iterations= 20
Calibration Max Change=0.05
Calibration Tolerance=0.2
Calibration Maximum=1.5
Calibration Minimum=0.5
Calibration Optimization Method= 1
WQ AD Non Conservative
WQ ULTIMATE=-1
WQ Max Comp Step=1HOUR
WQ Output Interval=15MIN
WQ Output Selected Increments= 0
WQ Create Restart=0
WQ Fixed Restart=0
WQ System Summary=0
WQ Write To DSS=0
Sorting and Armoring Iterations= 10
XS Update Threshold= 0.02
Bed Roughness Predictor= 0
Hydraulics Update Threshold= 0.02
Energy Slope Method= 1
Volume Change Method= 1
Sediment Retention Method= 0
Sediment TS Multiplier= 1
Warm Up Method= 0
XS Weighting Method= 0
Number of US Weighted Cross Sections= 1
Number of DS Weighted Cross Sections= 1
Upstream XS Weight=0
Main XS Weight=1
Downstream XS Weight=0
Number of DS XS's Weighted with US Boundary= 1
Upstream Boundary Weight= 1
Weight of XSs Associated with US Boundary= 0
Number of US XS's Weighted with DS Boundary= 1
Downstream Boundary Weight= 0.5
Weight of XSs Associated with DS Boundary= 0.5
Percentile Method= 0
Sediment Output Level= 3
Mass or Volume Output= 0
Output Increment Type= 1
Profile and TS Output Increment= 1
Transport Output Increment 1
XS Output Flag= 0
XS Output Increment= 10
Read HDF5 Sediment Hotstart= 0
Sediment Hotstart Type= 0
Write Gradation File= 0
Read Gradation Hotstart= 0
Write HDF5 File= 1
Write Binary Output= 1
Write DSS Sediment File= 0
DSS Sediment Output Type= 1
SV Curve= 0
Specific Gage Flag= 0
Subcell Erosion Methods= 0
Subcell Deposition Methods= 0
Advection Scheme= 1
Matrix Solver= 0
Implicit Weighting Factor= 1
Maximum Outer Loop Convergence Iterations= 5
Convergence Maximum Absolute= 0.001
Convergence RMSE= 0.0001
Grain Fractions Max Abs Error= 0.001
Max Subgrid Regions= 1
Max Subgrid Length Scale= 3.402823E+38
Initial Layer Thickness= 3.402823E+38
Min Layer Thickness= 3.402823E+38
Max Layer Thickness= 3.402823E+38
Number of Layers= 5

--- BUFALORNT2.f01 (steady flow) ---

Flow Title=Flow
Program Version=6.31
Number of Profiles= 1
Profile Names=F01pct
River Rch & RM=BUFALORNT2,Main            ,1097
     566
Boundary for River Rch & Prof#=BUFALORNT2,Main            , 1
Up Type= 0
Dn Type= 3
Dn Slope=0.01666
DSS Import GetInterval= 0
DSS Import GetPeak= 0
DSS Import FillOption= 0

--- BUFALORNT2.g01 (geometry) ---

Geom Title=Geometry
Program Version=6.31

River Reach=BUFALORNT2      ,Main
Reach XY= 30
1647242.37073748367639.1163978871647322.90043205 367643.24631089
1647366.26255006367647.3758958131647385.87865256367646.343745649
1647410.31298688367644.2787891481647522.50370739367614.338232234
1647551.06762664367600.5725117331647641.92177564367602.293308809
1647689.06964722367606.4228937331647704.90032423367604.702096641
1647721.07483256367599.8841928991647741.72374138367590.248057306
1647786.11800955367578.547293305 1647840.4929008367570.631954804
1647874.90720205 367567.53452006 1647905.5360778367560.651659817
 1647925.4966678367558.2425438911647999.14317405367531.743581146
1648027.01910256367526.9256773891648054.89470297367524.860720888
1648065.56298873367521.7632861441648085.17941931367510.750840977
1648105.13968122367493.8876857311648159.17041305367470.141670227
1648182.91610047367456.3759497261648220.11733479367441.463327114
1648236.78239808367440.3669413721648252.96010555 367444.58372356
 1648268.1362119367457.3474532071648284.68230113367478.412651062

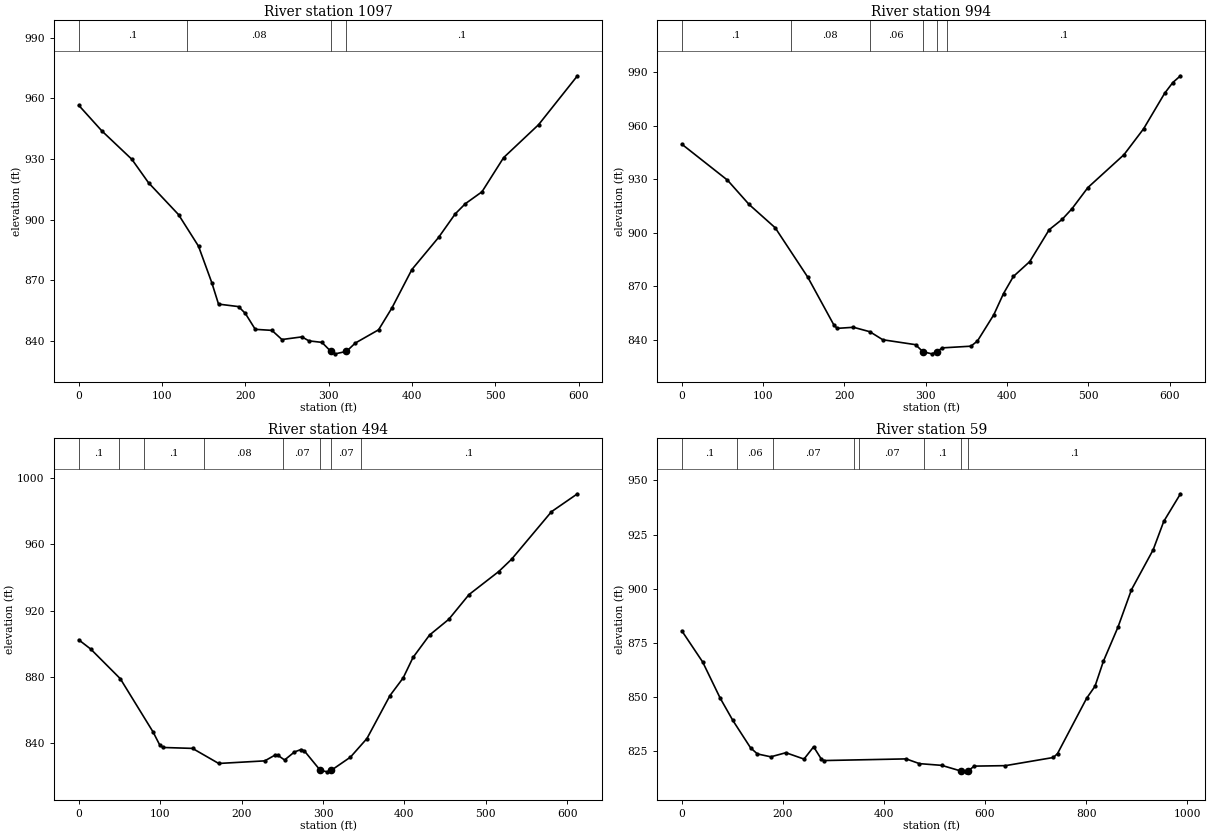
Type RM Length L Ch R = 1 ,1097    ,102.4,103.2,104.5
XS GIS Cut Line= 2
1647252.16122663367948.212518372 1647235.5943263367349.926781941
#Sta/Elev= 30
       0  956.51    27.7  943.86    63.7  929.81    83.7  918.22   119.7  902.46
   143.7  886.82   159.7  868.71   167.7  858.19   191.7  856.95   199.8  853.63
   211.8   845.7   231.8  845.19   243.8  840.66   267.8  841.97   276.2     840
   291.8  839.25  302.57834.7725   307.8  833.58   321.3834.7913   331.8   838.9
   359.8  845.47   375.8  856.26   399.8   875.3   431.8  891.16   451.8  902.82
   463.9  907.84   483.9  913.74   509.9  930.66   551.9  946.97   598.5  971.14
#Mann= 4 ,-1,0
       0      .1       0     130     .08       0  302.57    .045       0
   321.3      .1       0
Bank Sta=302.57,321.3
XS Rating Curve= 0 ,0
Exp/Cntr(USF)=0,0
Exp/Cntr=0.3,0.1

Type RM Length L Ch R = 1 ,994     ,501.5,500,497.8
XS GIS Cut Line= 6
1647322.29446217367951.0996978431647342.56509092367695.652374089
1647350.47583626367595.9658936711647357.00830351367521.248523429
1647360.49386084367433.6066383421647357.43940501367339.089767009
#Sta/Elev= 30
       0   949.6    56.1  929.47    82.8  915.79   114.9  902.74     155  875.02
   187.1  848.25   191.2  846.37   211.2  846.97   231.3  844.49   247.3  839.98
   287.5  837.23  296.66833.2759   307.5  832.09  314.15833.2665   320.1  835.42
   355.7  836.38   363.7  839.28   383.8  853.97   395.8   865.9   407.9  875.45
     428  883.77     452  901.68     468  907.49     480  913.41   499.6  925.29
     544  943.71   568.1   958.2     594  978.11   604.1  984.16   613.5  987.93
#Mann= 6 ,-1,0
       0      .1       0  133.75     .08       0  231.25     .06       0
  296.66    .045       0  314.15     .06       0  326.25      .1       0
Bank Sta=296.66,314.15
XS Rating Curve= 0 ,0
Exp/Cntr(USF)=0,0
Exp/Cntr=0.3,0.1

Type RM Length L Ch R = 1 ,494     ,433.1,435.3,436.2
XS GIS Cut Line= 6
 1647875.4442745367875.1077238321647863.97316884367782.019655421
1647852.63690542367695.2343959211647841.56967033367621.054426178
1647801.65538009367361.606782332 1647787.3995031367268.947190762
#Sta/Elev= 30
       0   902.3    14.7  896.73      51  878.87    91.3  846.71    99.3  839.01
   103.4   837.4   139.7  836.84   171.9  827.75   228.5  829.32   240.7   832.7
   244.7  832.65   252.8  829.84   264.9  834.68     273  836.17   277.1  835.33
  296.66823.6064   305.4   822.7  309.98823.5592   333.7  831.56     354   842.8
   382.3  868.71   398.5  879.35   410.6  891.69   430.9  905.21   454.5  914.68
   479.4  929.62   515.9  943.52   531.6  950.89   580.7  979.61   612.6  990.41
#Mann= 8 ,-1,0
       0      .1       0      50     .06       0      80      .1       0
  153.79     .08       0  251.31     .07       0  296.66    .045       0
  309.98     .07       0  346.32      .1       0
Bank Sta=296.66,309.98
XS Rating Curve= 0 ,0
Exp/Cntr(USF)=0,0
Exp/Cntr=0.3,0.1

Type RM Length L Ch R = 1 ,59      ,,,
XS GIS Cut Line= 4
1647958.72179797367909.5269739491648239.89938142367532.672072078
1648242.72580367367373.4694131911647896.00424671367287.084861457
#Sta/Elev= 30
       0  880.56    41.2  866.19    75.9  849.48     101  839.17     136  826.54
   149.5  823.71   176.1  822.38   205.9  824.27   241.8  821.34   260.8  827.01
   275.7  821.45   280.7  820.65   443.8  821.42   470.2  819.23   514.3  818.43
   552.2  815.82   562.3  815.44  566.77  815.82   578.3  818.08   640.4   818.3
   735.2  822.07   743.4  823.87   801.1  849.46   817.6  854.97   834.1  866.47
     863  882.25   889.7  899.54   932.7     918   953.6  931.09   986.7  943.84
#Mann= 8 ,-1,0
       0      .1       0     110     .06       0     180     .07       0
     340     .08       0     350     .07       0  480.19      .1       0
   552.2    .045       0  566.77      .1       0
Bank Sta=552.2,566.77
XS Rating Curve= 0 ,0
Exp/Cntr(USF)=0,0
Exp/Cntr=0.3,0.1
LCMann Table=0

Chan Stop Cuts=-1
Use User Specified Reach Order=0
Composite Channel Slope=5